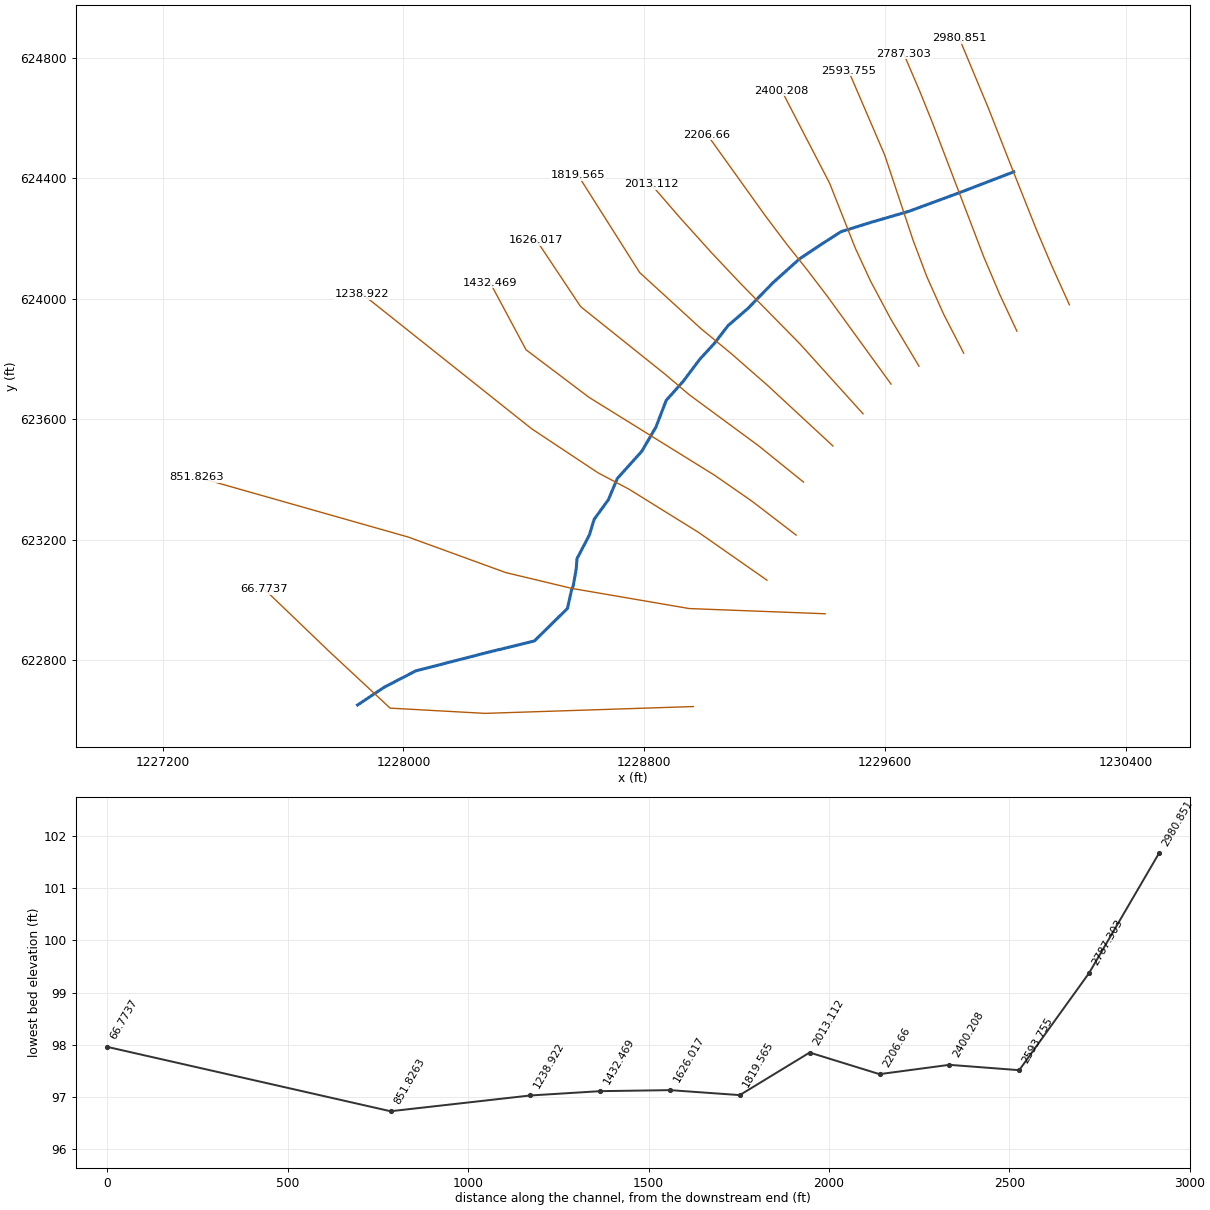
--- 272_ras.prj (project) ---

Proj Title=272
Current Plan=p01
Default Exp/Contr=0.3,0.1
English Units
Geom File=g01
Flow File=f01
Plan File=p01
Y Axis Title=Elevation
X Axis Title(PF)=Main Channel Distance
X Axis Title(XS)=Station
BEGIN DESCRIPTION:
RFD model 272 exported to HEC-RAS
END DESCRIPTION:

--- 272_ras.p01 (plan) ---

Plan Title=Plan 01
Program Version=4.10
Short Identifier=Plan 01
Geom File=g01
Flow File=f01
Subcritical Flow
Calc Critical at every XS
Secant Critical Depth

--- 272_ras.f01 (steady flow) ---

Flow Title=Flow 01
Program Version=5.01
Number of Profiles= 5
Profile Names=10yr,25yr,50yr,100yr,500yr
River Rch & RM=272,12,2980.851
  801.69 1065.03 1301.11 1547.53 2086.78
River Rch & RM=272,12,2787.303
  830.62  1109.2 1356.66 1622.08 2202.08
River Rch & RM=272,12,2593.755
  844.79  1130.9 1383.99  1658.9  2259.3
River Rch & RM=272,12,2400.208
  851.87 1141.77 1397.68 1677.38 2288.08
River Rch & RM=272,12, 2206.66
   855.5 1147.36 1404.71 1686.88 2302.91
River Rch & RM=272,12,2013.112
  861.42 1156.46 1416.19  1702.4 2327.13
River Rch & RM=272,12,1819.565
  865.51 1162.75  1424.1 1713.11 2343.88
River Rch & RM=272,12,1626.017
  867.03 1165.09 1427.06 1717.12 2350.14
River Rch & RM=272,12,1432.469
  959.71 1308.91 1608.63 1964.88 2741.56
River Rch & RM=272,12,1238.922
  980.41 1341.33 1649.63 2021.34 2831.79
River Rch & RM=272,12,851.8263
  986.26 1350.51 1661.26 2037.38 2857.48
Boundary for River Rch & Prof#=272,12,1
Up Type= 0
Dn Type= 2
Boundary for River Rch & Prof#=272,12,2
Up Type= 0
Dn Type= 2
Boundary for River Rch & Prof#=272,12,2
Up Type= 0
Dn Type= 2
Boundary for River Rch & Prof#=272,12,2
Up Type= 0
Dn Type= 2
Boundary for River Rch & Prof#=272,12,2
Up Type= 0
Dn Type= 2

--- 272_ras.g01 (geometry) ---

Geom Title=272
Program Version=4.10

River Reach=272,12
Reach XY= 30
1230026.73597869624421.7743261461229850.58056653624354.022250533
1229678.94195986624290.786980182 1229554.7298106624254.652540743
1229453.10168841624223.0349060151229389.86641175624182.383659422
 1229315.3391214624132.6988023671229227.26141402624053.654710755
1229143.70051178623967.8354109231229078.20683199623911.375345573
1229033.03877637623852.6568768921228983.35391554623798.455213755
1228929.15224874623726.1863292311228872.69217956623662.951055512
1228838.81613654623574.8733515591228791.38967755623493.570856065
1228710.08717793623403.2347507631228680.72794089623333.224268213
1228633.30148238623267.7305915361228617.49266201623215.787330121
1228576.30271453623137.0183653241228573.80271423623102.851708889
1228563.80271557623047.0183924141228558.37547424623033.568273783
 1228544.6310108622971.8421552781228434.85616305622863.809765488
1228278.03495201622825.4756916761228041.06067759 622764.48966518
1227936.51320359622710.4734702561227847.64785069622651.229901642

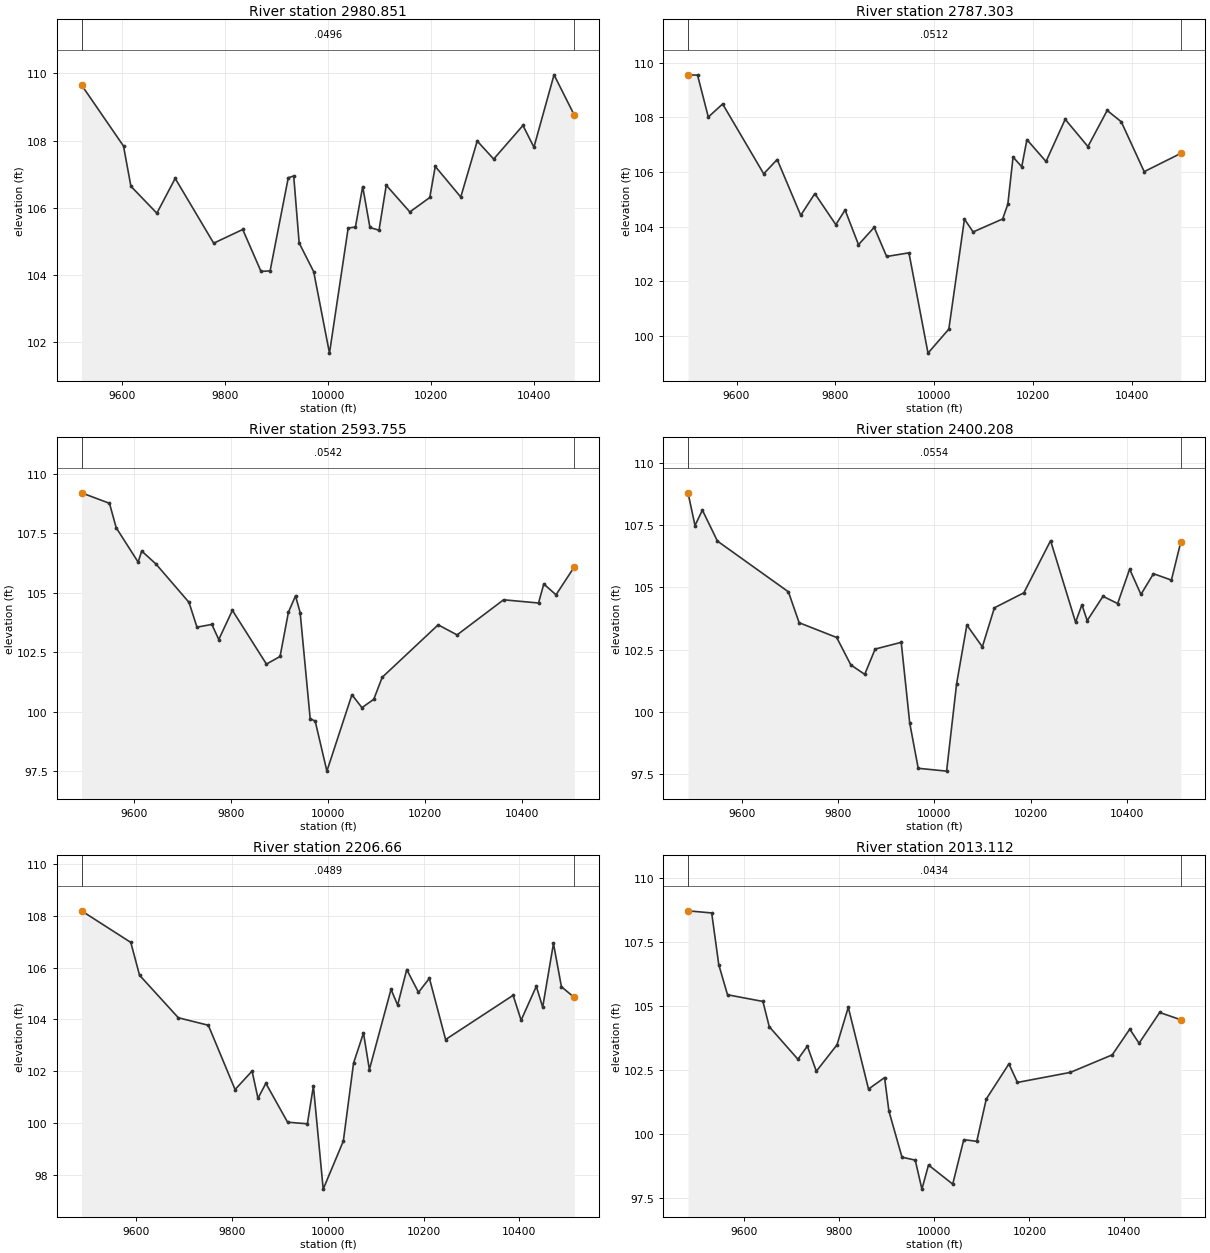
Type RM Length L Ch R = 1 ,2980.851,193.547700,193.547700,193.547700
XS GIS Cut Line= 6
1230211.59970267623980.1832768651230150.70649745624115.025131416
1230101.92446019624230.1731382851230026.16161213624420.482001477
1229943.12350712624631.837642013 1229845.8861881624865.148666519
#Sta/Elev= 30
9521.156109.65579602.702107.83619617.102106.6381  9667.5 105.8369703.147106.8733
9777.972104.94279834.406 105.351 9869.93104.10119887.627104.11789922.899 106.892
9933.493106.94489944.086104.94839972.337104.093910003.02 101.66710039.35105.3936
10053.45105.424510067.55106.629610081.65105.410210099.28105.328710113.38 106.669
10159.21105.873210197.98106.304310208.56 107.23110258.17106.318110290.16107.9865
10322.15107.449510379.02108.450510400.35107.802910439.44109.958710478.85108.7575
#Mann= 3 , 0 , 0
9521.156  0.0496       09521.156  0.0496       010478.85  0.0496       0
#XS Ineff= 2 , 0
       0                               0
Bank Sta=9521.156,10478.85
Exp/Cntr=0.3,0.1

Type RM Length L Ch R = 1 ,2787.303,193.547600,193.547600,193.547600
XS GIS Cut Line= 6
1230037.25569328 623892.684109781229980.37135357624014.259752984
1229926.58403294 624140.863943081229757.41810229624583.217908555
1229715.94870417624686.211891242 1229660.9787308624814.751411628
#Sta/Elev= 30
9501.897  109.559521.176 109.5399542.909 108.0079571.887108.48399654.894105.9315
9682.163106.45379729.752 104.4149758.269105.20779800.734104.07239819.435104.6091
9846.549103.33979878.267103.97549903.441102.90799948.523 103.0429987.09499.37496
10029.19100.254210060.77104.273810078.31103.806110137.97104.280210148.49104.8217
10159.02106.544910176.57106.190310187.09107.179810225.69106.381410264.43107.9245
 10310.4106.927110349.31108.248110377.78107.834210424.15106.010310498.11106.6777
#Mann= 3 , 0 , 0
9501.897  0.0512       09501.897  0.0512       010498.11  0.0512       0
#XS Ineff= 2 , 0
       0                10122.31       0
Bank Sta=9501.897,10498.11
Exp/Cntr=0.3,0.1

Type RM Length L Ch R = 1 ,2593.755,193.547700,193.547700,193.547700
XS GIS Cut Line= 6
1229860.56336802623819.6606207111229794.74030511 623947.37646227
1229738.41618979624072.858819512 1229692.5781073624194.237024482
1229598.31104762 624477.255085541229477.62818531624758.114845245
#Sta/Elev= 30
9492.466109.20159549.971108.76179563.864107.73429609.026106.29349616.408106.7572
9645.754106.21289713.733104.60469730.252103.56049760.853 103.6769775.125103.0415
9803.181104.26689873.321102.00969901.377102.32969918.638104.18979933.219104.8744
9942.754104.17399963.42499.720339973.75999.615219997.87497.5150110049.46100.7238
 10070.1100.179110094.46100.531910111.76 101.45410227.09103.658210266.03103.2354
10361.84104.710210433.86104.574610444.67 105.37310469.88104.919210507.55106.0924
#Mann= 3 , 0 , 0
9492.466  0.0542       09492.466  0.0542       010507.55  0.0542       0
#XS Ineff= 2 , 0
       0                10135.41       0
Bank Sta=9492.466,10507.55
Exp/Cntr=0.3,0.1

Type RM Length L Ch R = 1 ,2400.208,193.547700,193.547700,193.547700
XS GIS Cut Line= 6
1229712.14254117623776.3799898561229618.91453858623931.993290582
1229551.28984192624058.7445168041229500.55729495624168.517662617
1229415.41747729624383.5823253991229255.84758929624691.739921345
#Sta/Elev= 30
9487.731108.80579502.237107.4916 9517.62 108.1099548.925106.86539696.444104.8265
9718.755103.58429796.845102.98959826.207101.88829855.121101.50849876.807 102.525
9931.021102.79499948.72199.548669966.35597.7312910025.3797.6172110046.25101.1397
10067.48103.490710099.69102.614110124.74104.182910186.03104.787510241.58106.8822
10293.54103.604410306.72104.305810317.69103.668510350.57104.646410381.02104.3546
10405.97105.738310429.45104.721710455.53105.554510492.78105.297310512.27106.8302
#Mann= 3 , 0 , 0
9487.731  0.0554       09487.731  0.0554       010512.27  0.0554       0
#XS Ineff= 2 , 0
       0                10138.64       0
Bank Sta=9487.731,10512.27
Exp/Cntr=0.3,0.1

Type RM Length L Ch R = 1 , 2206.66,193.547700,193.547700,193.547700
XS GIS Cut Line= 6
1229619.23971593  623716.96155421229407.90088148624008.210342536
1229341.58784517624095.1182066131229272.07810461624182.422174075
 1229201.9360839624275.5377042051229008.53223189624545.550362138
#Sta/Elev= 30
 9485.26108.19629588.127106.97619606.392105.70829687.464104.06259750.129103.7735
9805.992101.2887  9841.5 102.0039853.815100.95089870.322101.52889915.717 100.026
 9957.0399.964219969.625101.42269990.10597.4389910032.1999.2974110053.51102.3088
10074.28103.4754 10086.6102.060910131.79105.161210145.63104.554310164.65105.9265
10189.17105.045310212.01105.589110245.82103.221510386.92 104.93210403.57103.9674
10435.35105.280310448.65104.471510471.18106.933710487.81105.262310514.73104.8468
#Mann= 3 , 0 , 0
 9485.26  0.0489       0 9485.26  0.0489       010514.73  0.0489       0
#XS Ineff= 2 , 0
       0                               0
Bank Sta=9485.26,10514.73
Exp/Cntr=0.3,0.1

Type RM Length L Ch R = 1 ,2013.112,193.547600,193.547600,193.547600
XS GIS Cut Line= 6
  1229526.254674623618.2470426061229316.62680768623850.486608746
1229121.37343922624048.9851015991229022.56020205624153.749078869
1228918.14355419624269.6670096611228822.56432749 624380.11796836
#Sta/Elev= 30
9481.294108.73019531.146 108.6479545.995106.62929564.421105.4497 9638.96105.1882
9652.333104.20159712.643102.92899732.575 103.4449751.411102.45969795.005103.4945
9818.685104.96079861.309101.76399895.086102.21279904.185100.90739931.74499.10091
9959.66898.986089973.69397.852559987.59298.7946910038.5698.0485910061.8699.78587
10089.22 99.721610109.26101.378410156.87 102.74710174.91102.023210286.17 102.415
10374.45103.101310411.34104.106110430.86103.555210474.24104.7575 10518.7104.4731
#Mann= 3 , 0 , 0
9481.294  0.0434       09481.294  0.0434       0 10518.7  0.0434       0
#XS Ineff= 2 , 0
       0                               0
Bank Sta=9481.294,10518.7
Exp/Cntr=0.3,0.1

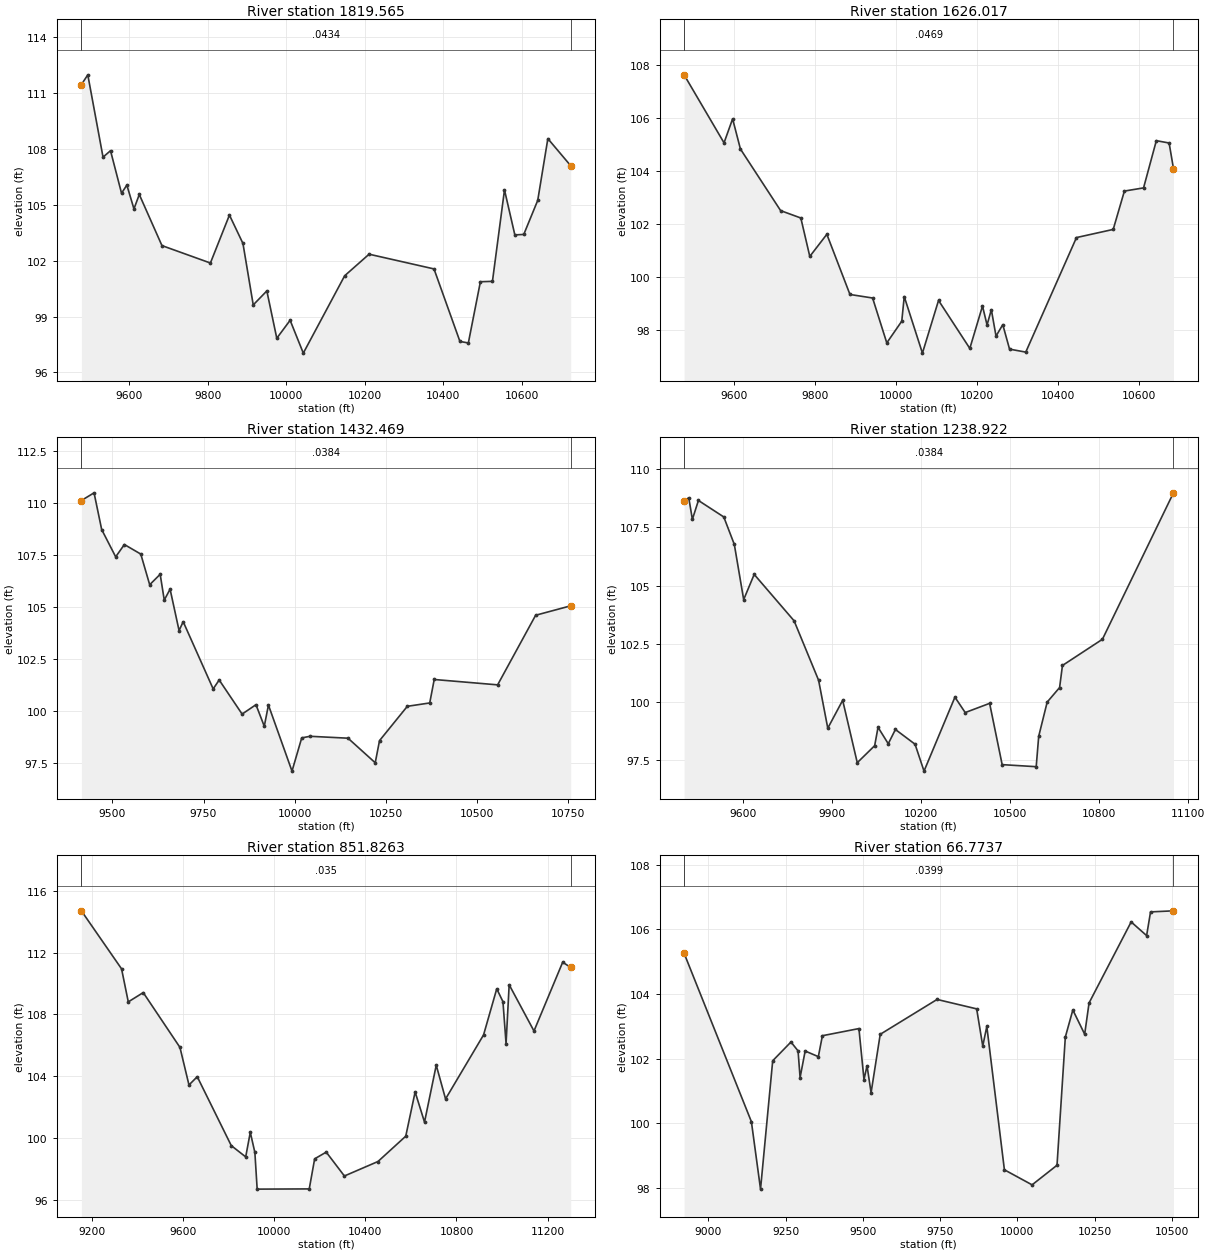
Type RM Length L Ch R = 1 ,1819.565,193.547700,193.547700,193.547700
XS GIS Cut Line= 6
1229426.32821596623511.3652533141229209.86238733623711.930649042
1229089.45310289623817.3763605061228987.49193892623901.530845821
1228784.44797513624087.2642171831228579.49736932624410.924503848
#Sta/Elev= 30
9478.564111.46589494.899 111.9919533.657107.56819552.739107.91499580.766105.6299
9594.324106.06599612.401 104.7869625.959105.56089683.653102.81539806.984 101.879
9855.436104.45549889.844102.9299 9916.0199.627169950.652100.38039975.95497.83714
10009.9298.8023610043.4797.0374710148.79101.194810210.93102.353110376.15101.5621
10442.1697.66542 10463.697.5835110494.26100.873510524.93 100.89410555.59105.8068
10581.96103.389910604.65103.415110640.21105.245510665.98108.562310724.23107.1049
#Mann= 3 , 0 , 0
9478.564  0.0434       09478.564  0.0434       010724.23  0.0434       0
#XS Ineff= 2 , 0
       0                10174.63       0
Bank Sta=9478.564,10724.23
Exp/Cntr=0.3,0.1

Type RM Length L Ch R = 1 ,1626.017,193.547700,193.547700,193.547700
XS GIS Cut Line= 6
1229328.60453084623391.4424204231229179.58571392623511.805441245
1228949.84096175623680.9541552361228869.22250232623749.363044873
1228588.38390669623974.1310965871228441.62942576624194.661062971
#Sta/Elev= 30
 9477.56107.61799576.048105.05519597.221105.95919616.484104.82299715.694102.5013
9765.497102.22389787.632100.77649829.682101.6097 9886.72 99.34259942.57499.20914
9977.57497.5179310014.53 98.336210020.6399.2631810065.5197.1325810105.2499.11792
10182.4197.3095110213.6898.9066210224.9198.1940710235.5498.7682910247.0597.77336
10263.7398.2055410280.4297.2830310320.4397.1708810445.51101.486710536.15101.7934
10563.74103.238210611.03103.358110642.56105.137310674.09105.049110684.81104.0866
#Mann= 3 , 0 , 0
 9477.56  0.0469       0 9477.56  0.0469       010684.81  0.0469       0
#XS Ineff= 2 , 0
       0                 10231.9       0
Bank Sta=9477.56,10684.81
Exp/Cntr=0.3,0.1

Type RM Length L Ch R = 1 ,1432.469,193.547700,193.547700,193.547700
XS GIS Cut Line= 6
1229303.97139603623215.4525419921229157.40246317623327.988911361
1229033.08507019623414.2411820291228616.02663684623673.002890125
1228407.21698925623830.6652464271228287.54172418624054.089826405
#Sta/Elev= 30
9415.041110.12469449.791110.49489470.675108.73119509.104107.41679532.965108.0088
 9577.95107.5499 9602.39106.07619631.167106.57869642.357105.3365 9658.33105.8635
9682.966103.87159694.268104.29829776.508101.06659792.988101.49599855.887 99.8559
9893.886100.30729916.69699.270439928.101100.2897 9992.7397.1129810019.3998.71136
10042.1798.7879310146.36 98.696510221.0197.5149810232.79 98.580210309.06100.2297
10370.48100.3912 10382.8101.519110556.74101.261210660.96 104.60810757.25 105.062
#Mann= 3 , 0 , 0
9415.041  0.0384       09415.041  0.0384       010757.25  0.0384       0
#XS Ineff= 2 , 0
       0                10330.73       0
Bank Sta=9415.041,10757.25
Exp/Cntr=0.3,0.1

Type RM Length L Ch R = 1 ,1238.922,387.095300,387.095300,387.095300
XS GIS Cut Line= 6
1229207.27494448623065.6322514711228979.56452382623224.654211342
1228749.21153897623367.733303279 1228646.4905633 623422.02259317
1228426.01822555623568.295955405 1227863.1247215624016.243724272
#Sta/Elev= 30
9400.985108.63859416.646108.77159428.859 107.8439449.213108.65559534.701107.9474
9570.199106.76819601.725104.39869637.191105.47979771.688103.48679854.302100.9321
  9885.298.873699935.409100.07269984.60297.3925510043.2498.1230910054.5998.91297
10089.04 98.206610113.1598.8188710179.3698.1860510209.5897.0302710313.75 100.207
10348.3999.5456910430.6699.9411110472.9497.3091310587.6897.22074 10596.198.52555
10624.6899.9952210666.54100.620610676.12101.568210810.88102.693411050.31108.9839
#Mann= 3 , 0 , 0
9400.985  0.0384       09400.985  0.0384       011050.31  0.0384       0
#XS Ineff= 2 , 0
       0                10368.05       0
Bank Sta=9400.985,11050.31
Exp/Cntr=0.3,0.1

Type RM Length L Ch R = 1 ,851.8263,785.052600,785.052600,785.052600
XS GIS Cut Line= 6
1229400.54871896622954.156069085 1228949.4254407622971.421850204
1228560.41422209623038.1232824921228339.37243807623091.024059534
1228016.26086298623208.7721321731227313.47539088623408.368721783
#Sta/Elev= 30
9153.175114.69059329.544110.94679359.087108.81329424.753 109.4149585.952105.8765
9625.547  103.459661.894103.9847 9811.2499.537489874.62398.809389894.742100.3957
9914.87299.097929924.93896.7284810153.6296.7425310177.3498.6841910228.1999.11715
10307.9197.5760410455.46 98.511610577.33100.145710618.52103.0007 10659.7 101.053
10711.18104.727410752.07102.549610918.95106.682510976.85109.657511004.09108.8262
11017.71106.121311031.34109.918811140.32106.934211266.32 111.37411301.69 111.034
#Mann= 3 , 0 , 0
9153.175   0.035       09153.175   0.035       011301.69   0.035       0
#XS Ineff= 2 , 0
       09898.212        10503.42       0
Bank Sta=9153.175,11301.69
Exp/Cntr=0.3,0.1

Type RM Length L Ch R = 1 , 66.7737,0.000000,0.000000,0.000000
XS GIS Cut Line= 5
1228962.82090682622646.0025279521228271.06512046622623.350575224
1227955.68024048622640.7751542481227755.29758197622827.218149573
1227537.49034443623036.313097611
#Sta/Elev= 30
 8921.47105.26029139.228100.04829168.772 97.96129208.163101.93379267.249102.5141
9290.228102.23939296.793101.41329313.206102.23539355.879102.0609 9369.01 102.709
9487.183102.92989503.596101.35149513.444 101.7799526.574100.94659556.118102.7521
9740.068103.83159868.215103.5396 9887.93102.38799901.074102.99689957.96598.55986
10047.5998.0935310128.2598.7003510155.14102.666710179.46103.505610217.74102.7553
10231.96103.723510368.18106.230510418.21105.807510430.93106.5408 10505.1106.5739
#Mann= 3 , 0 , 0
 8921.47  0.0399       0 8921.47  0.0399       0 10505.1  0.0399       0
#XS Ineff= 2 , 0
       09894.914        10204.91       0
Bank Sta=8921.47,10505.1
Exp/Cntr=0.3,0.1